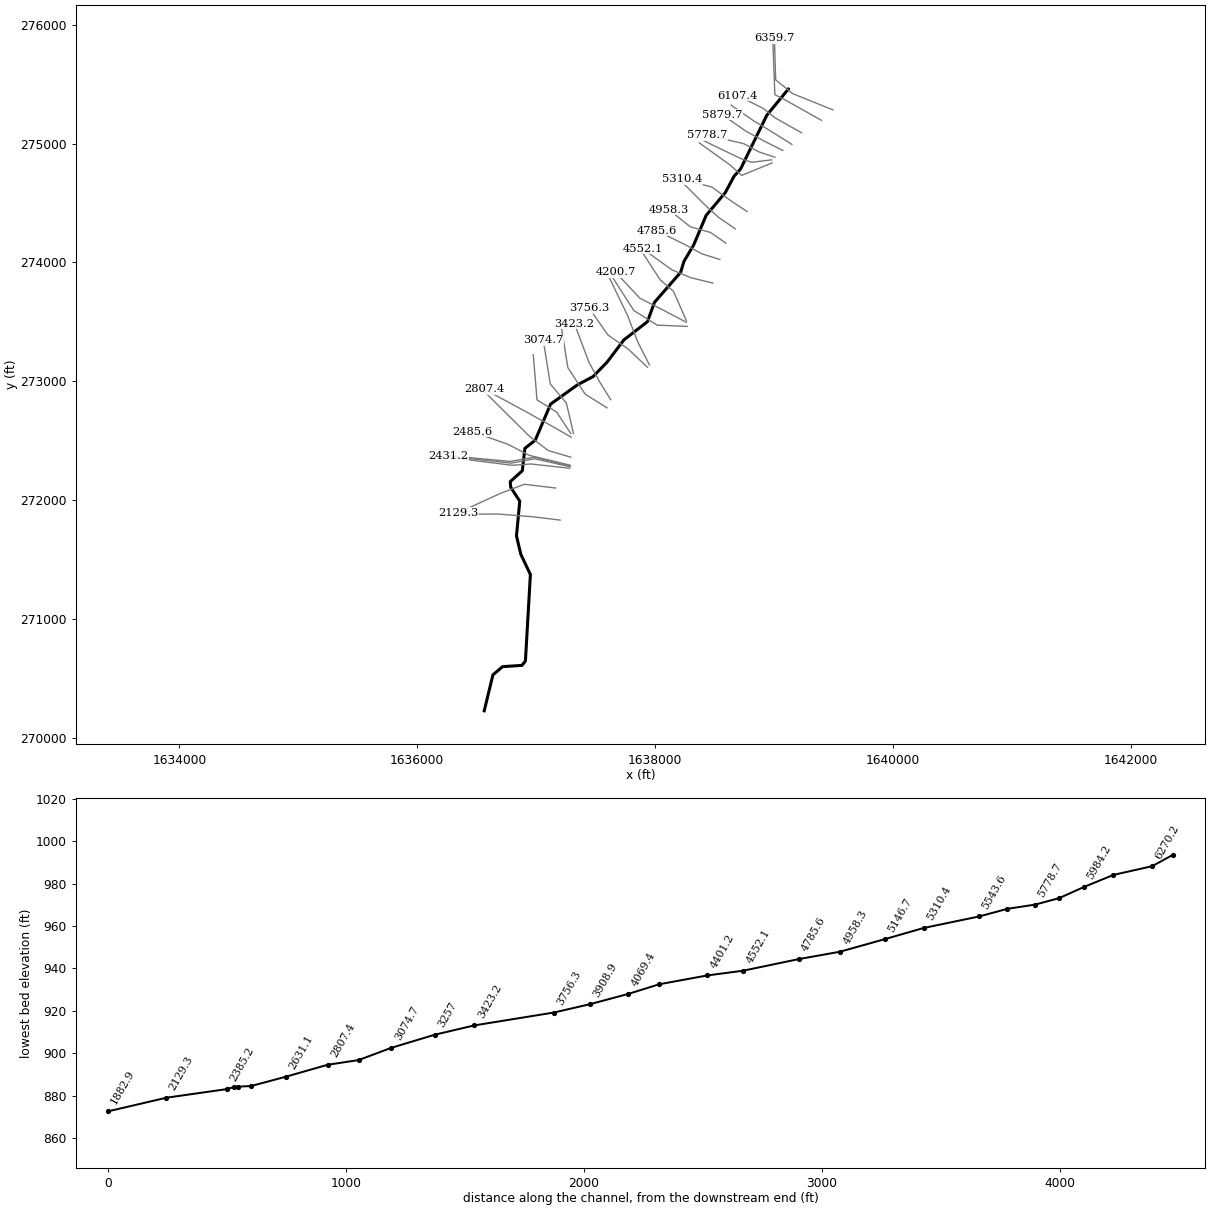
--- np1.prj (project) ---

Proj Title=np1
Current Plan=p01
Default Exp/Contr=0,0
English Units
Geom File=g01
Flow File=f01
Plan File=p01
BEGIN DESCRIPTION:
END DESCRIPTION:
DSS Export Rating Curves= 0
DSS Export Rating Curve Sorted= 0
DSS Export Volume Flow Curves= 0
DXF OffsetX= 0
DXF OffsetY= 0
DXF ScaleX= 0
DXF ScaleY= 0

--- np1.p01 (plan) ---

Plan Title=Floodplain
Program Version=4.00
Geom File=g01
Flow File=f01
K Sum by GR=0
Std Step Tol=0.01
Critical Tol=0.01
Num of Std Step Trials=20
Max Error Tol=0.3
Flow Tol Ratio=0.001
Split Flow NTrial=30
Split Flow Tol=0.02
Split Flow Ratio=0.02
Log Output Level=0
Friction Slope Method=1
Unsteady Friction Slope Method=2
Unsteady Bridges Friction Slope Method=1
Global Log Level=0
CheckData=False
Run HTab=0
Run UNet=0
Run PostProcess=0
UNET Theta=0
UNET Theta Warmup=0
UNET ZTol=0
UNET ZSATol=0
UNET MxIter=0
UNET MaxInSteps=0
UNET DtIC=0
UNET DtMin=0
UNET MaxCRTS=0
UNET WFStab=0
UNET SFStab=0
UNET WFX=0
UNET SFX=0
UNET DSS MLevel=0
UNET DZMax Abort=0
UNET Convert EG Bridges=0
UNET Use Existing IB Tables=0
UNET Froude Limit=0
UNET Froude Power=0
Write IC File=0
Echo Input=False
Echo Output=False
Write Detailed=0

--- np1.f01 (steady flow) ---

Flow Title=NFF Regression Equation
Program Version=4.00
Number of Profiles= 1
Profile Names=P100yr
River Rch & RM=np1,Main            ,6359.7
     320
River Rch & RM=np1,Main            ,6270.2
     320
River Rch & RM=np1,Main            ,5984.2
     366
River Rch & RM=np1,Main            ,5310.4
     397
River Rch & RM=np1,Main            ,2936.8
     440
River Rch & RM=np1,Main            ,2631.1
     519
River Rch & RM=np1,Main            ,260.5
     573
Boundary for River Rch & Prof#=np1,Main            , 1
Up Type= 0
Dn Type= 3
Dn Slope=0.012
DSS Import GetInterval= 0
DSS Import GetPeak= 0
DSS Import FillOption= 0

--- np1.g01 (geometry) ---

Geom Title=USGS 10m DEM
Program Version=4.00

River Reach=np1             ,Main
Reach XY= 30
      1639120.23      275457.664     1638939.517      275238.088
     1638718.453      274785.433     1638663.895      274724.984
     1638590.251      274587.729     1638429.001      274395.346
      1638325.08      274148.835     1638242.357      274008.451
     1638214.825      273917.244     1637994.869      273665.154
     1637935.032       273501.71     1637737.792      273349.348
     1637597.065      273163.189     1637478.499      273040.745
     1637347.272      272971.377      1637121.14      272809.154
     1636992.023      272505.415     1636904.896      272437.401
     1636883.391      272248.844     1636782.064      272157.596
     1636785.388      272111.056     1636861.847      271993.045
     1636834.396      271701.074      1636870.47      271547.569
      1636951.31      271376.451     1636909.452      270649.668
      1636880.69      270612.694     1636717.307      270601.955
     1636636.146      270532.747     1636563.127      270230.647

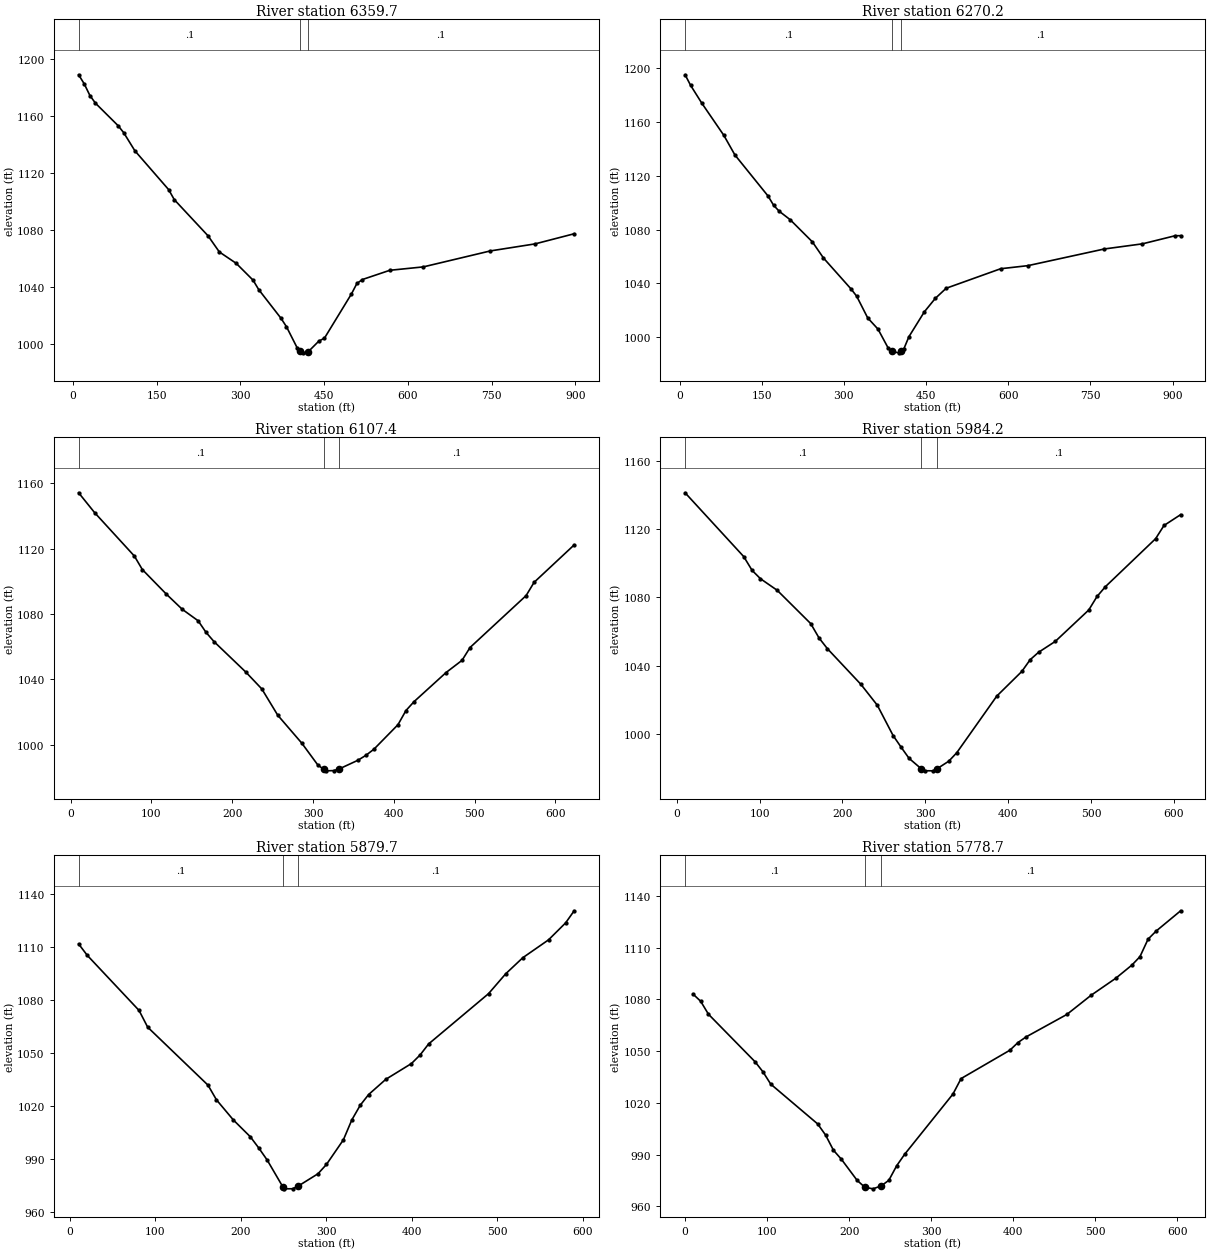
Type RM Length L Ch R = 1 ,6359.7  ,84.3,89.5,94.7
XS GIS Cut Line= 4
     1639494.073      275283.401     1639157.378      275419.121
     1639013.889      275535.243     1639003.367      275885.436
#Sta/Elev= 30
    10.1 1188.67    20.2 1182.25    30.3 1174.14    40.3 1168.74    80.7 1153.05
    90.8 1148.12   110.9 1135.39   171.4 1108.17   181.5 1101.15     242 1075.79
   262.2 1064.49   292.4 1056.53   322.7  1044.7   332.8 1038.09   372.7    1018
   382.5 1012.09   401.9  997.11  407.22  995.25   411.6  993.78   421.6  994.61
   440.7 1002.08   450.5 1004.03     499 1035.11   508.7  1042.4   518.5 1045.16
   567.6 1051.63   627.7 1054.02   747.8 1065.21   827.9 1070.14     898 1077.24
#Mann= 3 , 0 , 0
    10.1      .1       0  407.22    .045       0   421.6      .1       0
Bank Sta=407.22,421.6
XS Rating Curve= 0 ,0
Exp/Cntr=0.3,0.1

Type RM Length L Ch R = 1 ,6270.2  ,167.8,162.8,157.9
XS GIS Cut Line= 4
     1639398.203       275195.41     1639098.772      275363.512
     1639006.842       275410.79     1638989.769      275878.323
#Sta/Elev= 30
    10.1 1195.11    20.2 1187.22    40.4 1174.11    80.8 1150.07     101 1135.48
   161.6 1104.88   171.7 1098.02   181.8 1093.63     202 1087.28   242.4 1070.84
   262.6 1058.85   313.1 1035.75   323.2 1030.45   343.4 1014.26   362.2 1005.92
     381  991.68  387.83  989.33   399.8  988.28  403.89  989.49   409.2  991.06
   418.6 1000.26   446.8 1018.79   466.7 1028.75   486.6 1036.31   586.1 1050.84
   635.9 1053.14   775.3 1065.54   844.9 1069.36   904.7  1075.4   914.6 1075.42
#Mann= 3 , 0 , 0
    10.1      .1       0  387.83    .045       0  403.89      .1       0
Bank Sta=387.83,403.89
XS Rating Curve= 0 ,0
Exp/Cntr=0.3,0.1

Type RM Length L Ch R = 1 ,6107.4  ,119.8,123.2,126.5
XS GIS Cut Line= 4
     1639231.415      275090.347     1639008.155      275216.423
     1638907.032      275296.534     1638694.278      275402.911
#Sta/Elev= 30
     9.9 1154.08    29.6    1142    78.9 1115.41    88.8 1107.14   118.3 1092.24
   138.1  1082.9   157.8 1075.87   167.6 1068.79   177.5 1063.12     217 1044.44
   236.7 1034.18   256.4 1018.13   286.2 1001.04     306  987.73  313.26  985.09
   315.9  984.16   325.9  984.31   332.2  985.27   355.6  990.62   365.6  993.67
   375.5  997.41   405.2 1012.36   415.1 1021.02   425.1 1026.45   464.7 1044.22
   484.5 1051.69   494.4 1059.52   563.8 1091.24   573.7 1099.36   623.3 1122.22
#Mann= 3 , 0 , 0
     9.9      .1       0  313.26    .045       0   332.2      .1       0
Bank Sta=313.26,332.2
XS Rating Curve= 0 ,0
Exp/Cntr=0.3,0.1

Type RM Length L Ch R = 1 ,5984.2  ,103.5,104.6,105.6
XS GIS Cut Line= 4
     1639149.991      274993.163     1638952.997      275116.613
     1638829.547      275190.157      1638639.12        275322.8
#Sta/Elev= 30
    10.1 1141.24    80.9 1103.87      91  1095.8   101.1 1090.92   121.3 1084.15
   161.7 1064.68   171.8 1056.24   181.9 1049.96   222.4 1029.05   242.1 1016.89
   261.2  999.11   270.8  992.35   280.4  985.81  295.13  979.71   299.5  978.55
   309.1  978.49  314.07  979.67   328.3  984.12   337.9  989.03   386.3 1022.25
   416.5 1036.66   426.6 1043.55   436.7 1047.87   456.9 1054.25   497.3 1072.63
   507.3 1080.55   517.4 1086.28     578 1114.37   588.1 1122.09   608.2 1128.44
#Mann= 3 , 0 , 0
    10.1      .1       0  295.13    .045       0  314.07      .1       0
Bank Sta=295.13,314.07
XS Rating Curve= 0 ,0
Exp/Cntr=0.3,0.1

Type RM Length L Ch R = 1 ,5879.7  ,101,101,100.9
XS GIS Cut Line= 4
      1639073.82      274941.945     1638929.358      275014.176
     1638763.883       275103.48     1638566.889      275241.376
#Sta/Elev= 30
    10.1 1111.69    20.2 1105.26    80.8  1074.1    90.9 1064.63   161.5 1031.83
   171.4 1023.54   191.2 1012.14     211 1002.66   220.9  996.31   230.8  989.45
  248.87  974.49   250.6   973.2   260.5  973.25  266.62  974.64   290.2  981.72
   300.1  986.99   319.9  1000.9   329.8 1012.18   339.7 1020.52   349.5 1026.55
   369.6 1035.15   399.6 1044.07   409.7 1048.91   419.7 1055.16   489.8 1083.59
   509.9 1094.83   529.9 1103.92     560 1114.02     580 1123.62     590 1130.46
#Mann= 3 , 0 , 0
    10.1      .1       0  248.87    .045       0  266.62      .1       0
Bank Sta=248.87,266.62
XS Rating Curve= 0 ,0
Exp/Cntr=0.3,0.1

Type RM Length L Ch R = 1 ,5778.7  ,112.8,117.1,121.4
XS GIS Cut Line= 4
     1639007.249      274885.078     1638872.269      274930.174
     1638745.123      274999.134     1638435.967      275070.252
#Sta/Elev= 30
     9.5 1083.15      19  1078.9    28.5 1071.38    85.4 1043.79    94.9 1038.02
   104.4 1030.87   161.6  1007.8   171.2 1001.41   180.9  992.52   190.5  987.35
   209.8  975.04   219.1   971.1   229.1  970.15   239.1  971.86   248.4   975.1
     258  983.55   267.7  990.19   326.6 1025.12   336.5 1034.08     396 1050.52
   405.9 1054.99   415.8 1058.25   465.4 1071.24   495.1 1082.41   524.9 1092.17
   544.7 1099.85   554.6 1104.77   564.5 1114.93   574.4 1119.64   604.2 1131.37
#Mann= 3 , 0 , 0
       0      .1       0   219.1    .045       0   239.1      .1       0
Bank Sta=219.1,239.1
XS Rating Curve= 0 ,0
Exp/Cntr=0.3,0.1

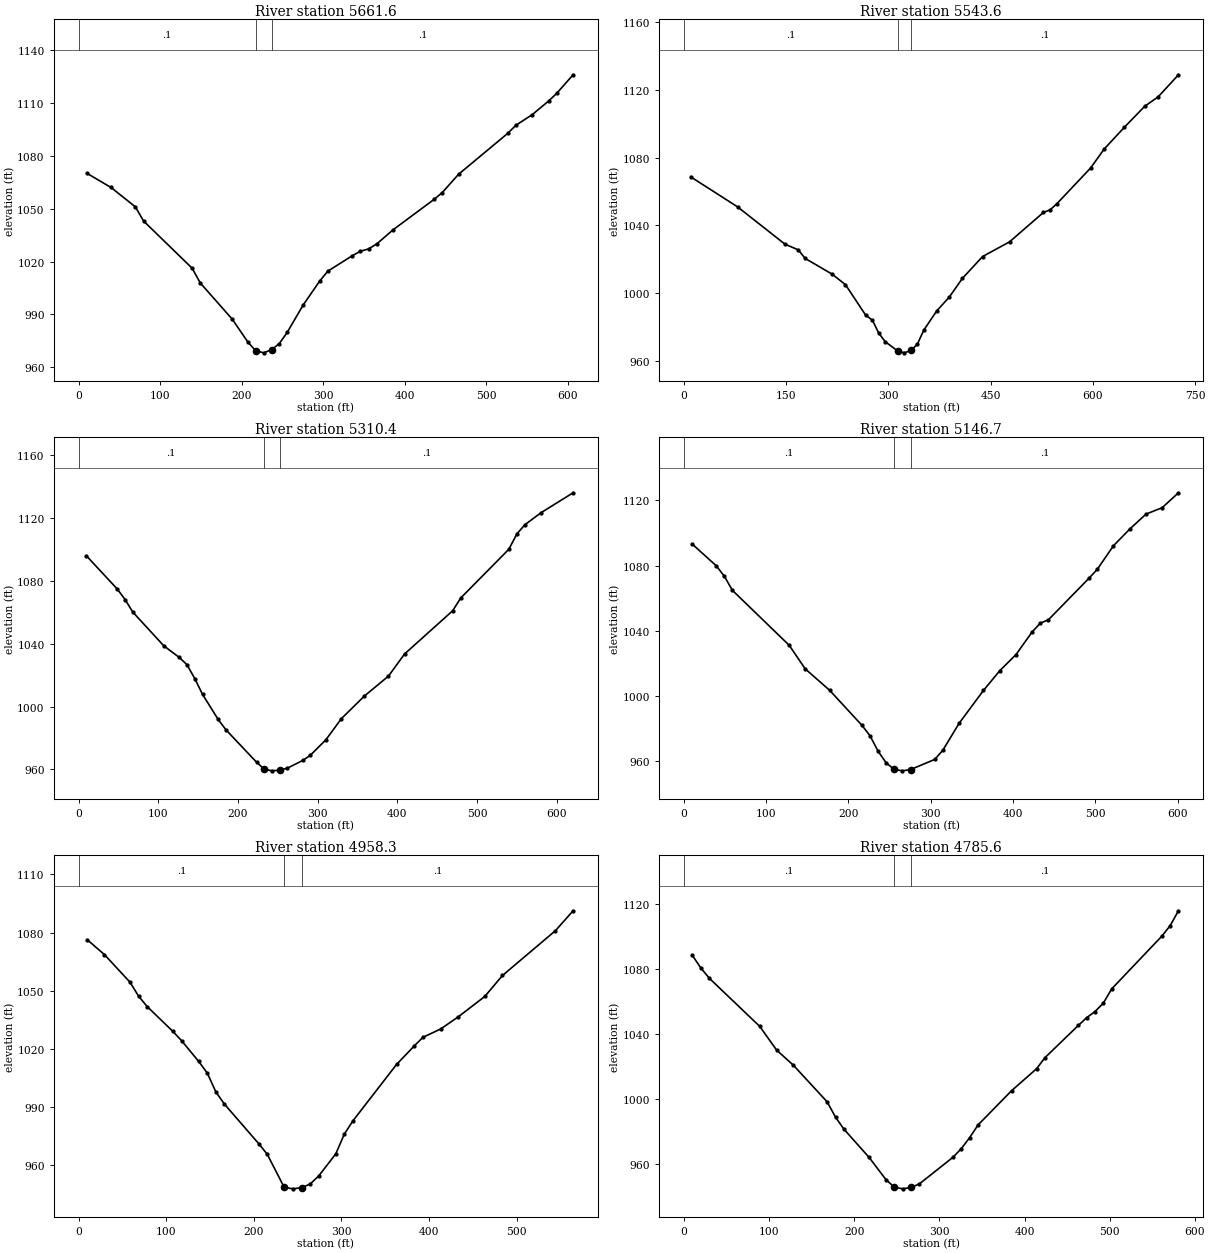
Type RM Length L Ch R = 1 ,5661.6  ,128.1,118,108
XS GIS Cut Line= 4
      1638980.02       274862.65     1638811.928      274842.536
     1638720.699      274873.425     1638413.251      275021.403
#Sta/Elev= 30
      10 1070.21    39.8  1062.1    69.7 1051.09    79.7 1043.06   139.4 1016.19
   149.4  1007.8   188.6  987.23   207.8  974.23   217.1  969.43   227.1  968.14
   237.1     970   246.3  973.41     256  979.77   275.6  995.32   295.7 1008.82
   305.7  1014.5   335.9 1023.34   345.9 1025.87   355.9  1027.2     366 1030.08
     386 1038.08   436.2 1055.33   446.2 1059.19   466.3 1069.62   526.5 1092.82
   536.6 1097.44   556.6 1103.47   576.7 1111.19   586.7  1115.6   606.8 1126.13
#Mann= 3 , 0 , 0
       0      .1       0   217.1    .045       0   237.1      .1       0
Bank Sta=217.1,237.1
XS Rating Curve= 0 ,0
Exp/Cntr=0.3,0.1

Type RM Length L Ch R = 1 ,5543.6  ,230.8,233.2,235.6
XS GIS Cut Line= 4
     1638984.516      274836.882     1638728.601      274732.182
     1638629.927      274819.809     1638372.521      275004.983
#Sta/Elev= 30
     9.9 1068.59      79 1050.75   148.1 1028.82   167.9 1025.39   177.8 1020.38
   217.3 1011.09     237 1004.86   266.6  986.86   276.5  983.86   285.9  976.17
   295.4  971.13   313.6  965.65   323.6  964.55   333.6  966.08   342.5  969.66
   351.9  977.96   370.8  989.27   389.6  997.64   408.5 1008.53   438.2 1021.46
   477.8 1030.17   527.4 1047.51   537.3 1049.08   547.2 1052.69   596.7 1073.81
   616.6 1085.01   646.3  1097.9     676 1110.26   695.8 1115.86   725.6 1128.91
#Mann= 3 , 0 , 0
       0      .1       0   313.6    .045       0   333.6      .1       0
Bank Sta=313.6,333.6
XS Rating Curve= 0 ,0
Exp/Cntr=0.3,0.1

Type RM Length L Ch R = 1 ,5310.4  ,166.2,163.7,161.1
XS GIS Cut Line= 4
     1638773.076      274428.448      1638619.42      274530.884
     1638478.898      274633.321     1638225.433      274698.986
#Sta/Elev= 30
     9.7    1096    48.6 1074.76    58.3  1068.1      68 1060.15   106.9 1038.66
   126.4 1031.23   136.1 1026.59   145.8 1017.77   155.5 1007.77     175  991.91
   184.7   985.3   223.3   964.6   232.6  960.29   242.6  959.11   252.6  959.56
     262  960.84   281.3  965.74   290.9  969.07   310.3  978.89   329.6  992.27
   358.6 1006.72   388.8  1019.4   408.9 1033.44   469.3 1060.97   479.4 1069.07
   539.8 1100.12   549.9 1109.89     560 1115.74   580.1 1123.34   620.4 1136.04
#Mann= 3 , 0 , 0
       0      .1       0   232.6    .045       0   252.6      .1       0
Bank Sta=232.6,252.6
XS Rating Curve= 0 ,0
Exp/Cntr=0.3,0.1

Type RM Length L Ch R = 1 ,5146.7  ,176.9,188.4,199.9
XS GIS Cut Line= 4
     1638674.579      274282.672     1638536.683      274377.229
     1638434.246       274469.16     1638224.119      274677.973
#Sta/Elev= 30
     9.8 1093.32    39.3 1079.83    49.2 1073.35      59 1064.71   127.9 1031.01
   147.5 1016.46     177 1003.37   216.4  981.78   226.2  975.38     236  965.88
   245.9  958.68   255.5  954.72   265.5  953.82   275.5  954.62   304.8  960.82
   314.7  966.47   334.5  983.05   364.1 1003.24   383.8 1015.31   403.6 1025.26
   423.3 1039.23   433.2 1044.56   443.1  1046.7   492.5 1072.27   502.3 1077.59
   522.1 1092.16   541.8 1102.36   561.6 1111.59   581.3 1115.55   601.1 1124.71
#Mann= 3 , 0 , 0
       0      .1       0   255.5    .045       0   275.5      .1       0
Bank Sta=255.5,275.5
XS Rating Curve= 0 ,0
Exp/Cntr=0.3,0.1

Type RM Length L Ch R = 1 ,4958.3  ,178.4,172.8,167.1
XS GIS Cut Line= 4
     1638594.468      274163.162     1638465.765      274252.466
     1638296.351      274299.745     1638115.116      274444.207
#Sta/Elev= 30
     9.8 1076.33    29.4 1068.69    58.7 1054.41    68.5 1047.19    78.3 1041.85
   107.7    1029   117.5 1024.28   137.1 1013.54   146.9 1007.55   156.7  997.81
   166.4  991.58   205.5  971.21   215.3   965.7   234.6  948.69   244.6  947.89
   254.6  948.52   264.1  950.33   273.9  954.49   293.5  965.92   303.2  976.06
     313  982.92   362.8 1011.99   382.9  1021.5     393 1026.02   413.2 1030.29
   433.3 1036.58   463.5 1047.05   483.7 1057.87   544.2    1081   564.3 1091.23
#Mann= 3 , 0 , 0
       0      .1       0   234.6    .045       0   254.6      .1       0
Bank Sta=234.6,254.6
XS Rating Curve= 0 ,0
Exp/Cntr=0.3,0.1

Type RM Length L Ch R = 1 ,4785.6  ,230.8,233.5,236.1
XS GIS Cut Line= 4
     1638544.563      274025.267     1638393.534      274072.545
     1638246.445      274152.656     1638017.933      274265.599
#Sta/Elev= 30
     9.9 1088.38    19.8 1080.61    29.7 1074.32      89 1044.57   108.8 1029.98
   128.6 1020.57   168.1  998.09     178  988.59   187.8  981.24   217.4  963.79
   237.1  950.16   246.8  945.51   256.8  944.42   266.8  945.29   276.5   947.5
   315.9   963.9   325.7  969.23   335.5  976.05   345.4  983.86   384.6 1004.89
     414 1018.47   423.8 1025.26     463 1045.15   472.8 1049.95   482.6 1053.71
   492.4 1058.91   502.2  1067.7     561 1100.17   570.8 1106.64   580.6 1115.86
#Mann= 3 , 0 , 0
       0      .1       0   246.8    .045       0   266.8      .1       0
Bank Sta=246.8,266.8
XS Rating Curve= 0 ,0
Exp/Cntr=0.3,0.1

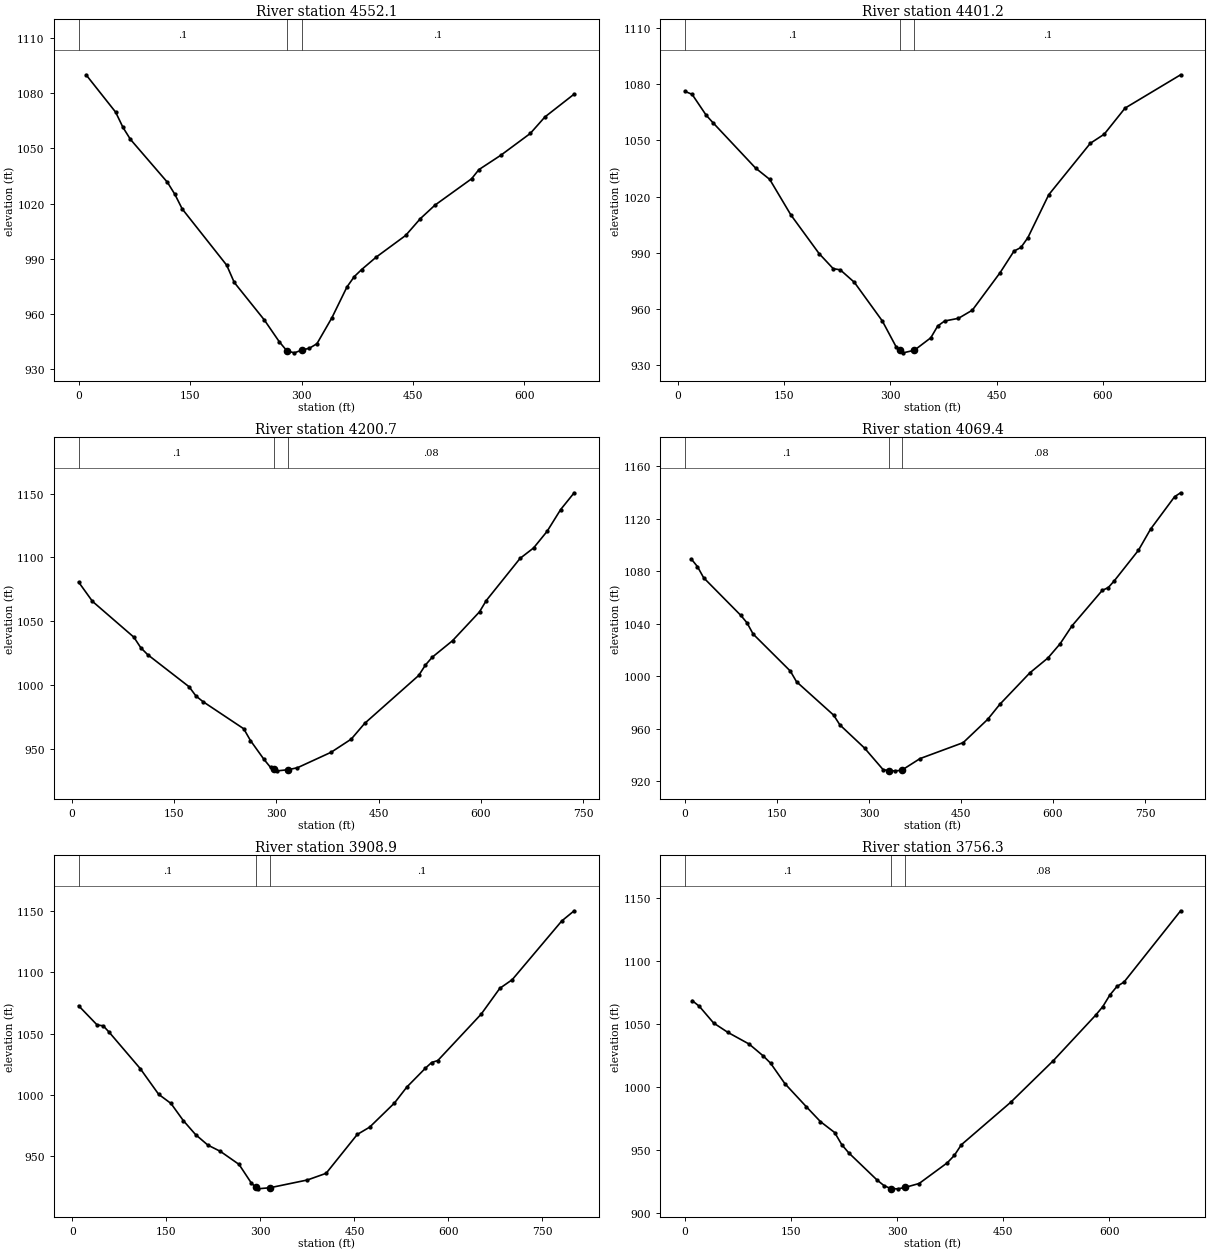
Type RM Length L Ch R = 1 ,4552.1  ,159.1,150.9,142.8
XS GIS Cut Line= 4
     1638485.465      273826.959     1638301.604      273871.611
     1638142.695      273937.276     1637894.483      274115.884
#Sta/Elev= 30
      10 1089.92    49.8 1069.63    59.7 1061.33    69.7 1054.86   119.5 1031.54
   129.5 1025.02   139.4 1017.08   199.3  986.51   209.4  977.19   249.9   956.8
   270.1  944.92   280.3  940.01   290.3  938.94   300.3  940.42   310.6  941.45
   320.7  943.89   340.9  958.02   361.1   974.7     371  980.35   380.9  984.18
   400.6  990.96   440.1 1002.68   459.8 1011.77   479.5 1019.12   528.8 1033.44
   538.7 1038.43   568.3 1046.26   607.8 1058.05   627.5 1067.01   666.9 1079.43
#Mann= 3 , 0 , 0
       0      .1       0   280.3    .045       0   300.3      .1       0
Bank Sta=280.3,300.3
XS Rating Curve= 0 ,0
Exp/Cntr=0.3,0.1

Type RM Length L Ch R = 1 ,4401.2  ,194.4,200.5,206.6
XS GIS Cut Line= 4
     1638262.938      273511.335     1638154.709      273757.486
     1638043.605      273853.264     1637882.698      274099.415
#Sta/Elev= 30
      10 1076.11    19.9 1074.56    39.8 1063.41    49.8 1059.26   109.5 1035.24
   129.5  1029.2   159.3 1010.28   199.2  989.64   219.1  981.61   229.1  980.96
     249  974.31   288.5  953.68     308  939.89  313.65  938.08   317.8   936.7
  333.73  938.08   356.9  944.72   366.7  951.02   376.5  953.68     396  955.11
   415.6  959.46   454.8  979.47   474.4  990.96   484.2  992.89     494  998.13
   523.4 1020.98   582.2 1048.46   601.8  1053.3   631.2 1067.21   709.7 1084.99
#Mann= 3 , 0 , 0
      10      .1       0  313.65    .045       0  333.73      .1       0
Bank Sta=313.65,333.73
XS Rating Curve= 0 ,0
Exp/Cntr=0.3,0.1

Type RM Length L Ch R = 1 ,4200.7  ,133.6,131.3,129
XS GIS Cut Line= 4
     1638262.205      273497.323     1638065.211      273601.073
     1637872.157       273699.57     1637668.597      273916.263
#Sta/Elev= 30
    10.1 1080.62    30.4 1065.51    91.1 1037.41   101.2 1029.17   111.3 1023.72
     172  998.55   182.2  991.24   192.3  986.91   252.2  965.56   262.1  956.29
   281.8   941.6   291.6  935.19  297.13  933.75   301.5  932.56  317.22  933.43
     331  935.01   380.3  947.13   409.8  957.44   429.5  969.78   508.7 1007.37
   518.7 1015.62   528.6 1021.71   558.3 1034.64   597.9  1057.3   607.8 1066.15
   657.4 1099.25   677.2 1107.42     697 1120.45   716.9 1137.57   736.7  1150.7
#Mann= 3 , 0 , 0
    10.1      .1       0  297.13    .045       0  317.22     .08       0
Bank Sta=297.13,317.22
XS Rating Curve= 0 ,0
Exp/Cntr=0.3,0.1

Type RM Length L Ch R = 1 ,4069.4  ,176.9,160.5,144.1
XS GIS Cut Line= 4
     1638269.528      273462.676     1638017.376      273473.182
     1637821.258      273595.756     1637646.152      273868.921
#Sta/Elev= 30
    10.1 1089.45    20.2  1083.6    30.3 1075.11    90.9 1046.44   100.9 1040.82
     111  1032.2   171.6 1004.02   181.7  995.89   242.3   970.4   252.4     963
   292.6  945.33   322.8  928.94   332.9     928   342.9  927.97   352.9  928.33
   383.1   937.3   453.5  949.47   493.5  967.24   513.1  978.59   562.3  1002.7
   591.8 1014.04   611.5 1024.79   631.1 1038.59   680.3 1065.54   690.1 1067.65
     700 1072.86   739.3  1096.1     759 1112.15   798.3 1136.96   808.1 1139.91
#Mann= 3 , 0 , 0
       0      .1       0   332.9    .045       0   352.9     .08       0
Bank Sta=332.9,352.9
XS Rating Curve= 0 ,0
Exp/Cntr=0.3,0.1

Type RM Length L Ch R = 1 ,3908.9  ,137.5,152.6,167.7
XS GIS Cut Line= 4
     1637952.587       273138.73     1637854.528      273331.346
     1637768.726      273553.731     1637618.135      273865.419
#Sta/Elev= 30
     9.8 1072.75    39.3 1057.07    49.1 1056.35    58.9 1050.91   108.1 1021.41
   137.5  1000.4   157.2   992.9   176.8  978.96   196.5  967.44   216.1  958.87
     236  953.77   265.8  943.11   285.7  927.68  293.11  924.31   295.6  923.14
   315.5  924.07     375  930.39   404.8  935.83   454.5  967.58   474.3  973.56
   513.8  993.23   533.6  1006.3   563.3 1021.74   573.2 1026.36   583.1    1028
   652.3 1065.91     682 1086.99   701.8 1094.04   780.9 1142.05   800.7 1150.36
#Mann= 3 , 0 , 0
     9.8      .1       0  293.11    .045       0   315.5      .1       0
Bank Sta=293.11,315.5
XS Rating Curve= 0 ,0
Exp/Cntr=0.3,0.1

Type RM Length L Ch R = 1 ,3756.3  ,345.1,333.1,320.8
XS GIS Cut Line= 4
     1637935.076      273119.468     1637773.979      273271.811
     1637602.376      273390.882     1637448.283      273613.267
#Sta/Elev= 30
    10.1  1068.8    20.2 1064.23    40.3 1051.01    60.5 1043.55    90.7 1034.22
   110.9 1024.65   120.9 1019.09   141.1 1002.86   171.3  984.58   191.5  972.61
   211.6  963.94   221.7  954.25   231.7  947.69   271.5  926.24   281.4  921.75
   291.3  919.31   301.3  919.18   311.3  920.32   331.1  923.42   370.9  939.85
   380.9  945.73   390.8  954.19   460.7  988.01   520.8 1020.97   580.9 1057.25
   590.9 1063.97   600.9 1073.19     611 1080.06     621 1083.53   701.1  1140.2
#Mann= 3 , 0 , 0
       0      .1       0   291.3    .045       0   311.3     .08       0
Bank Sta=291.3,311.3
XS Rating Curve= 0 ,0
Exp/Cntr=0.3,0.1

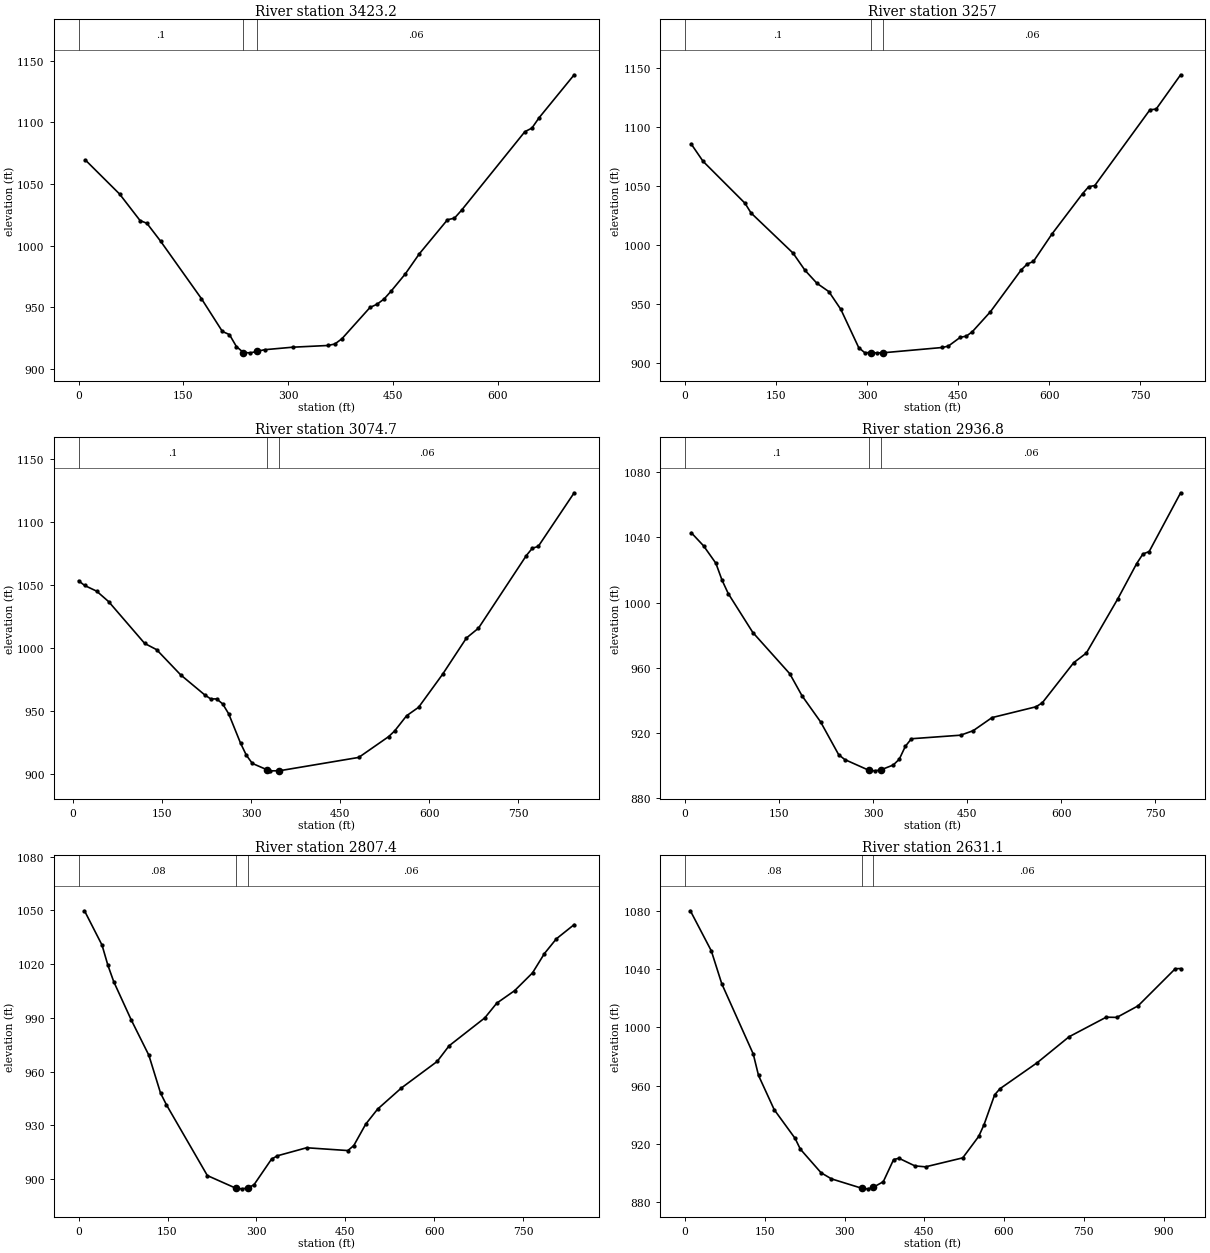
Type RM Length L Ch R = 1 ,3423.2  ,163.8,166.1,168.8
XS GIS Cut Line= 4
      1637626.89      272846.304     1637528.831      273003.899
     1637443.029      273163.245     1637322.207      273483.688
#Sta/Elev= 30
     9.8 1069.35    58.6 1041.86    87.9 1020.37    97.7 1018.14   117.2  1003.7
   175.8  956.99   205.7  930.46   215.8  927.91   225.8  918.19   235.9  913.34
   245.9  913.12   255.9  914.39     266  915.65   306.3  917.69   356.5  919.08
   366.6  920.27   376.7  924.51     417  949.93     427  952.52   437.1  956.78
   447.2  963.17   467.3  976.99   487.5  993.39   527.8 1021.02   537.8 1022.31
   547.9 1028.71   638.5 1092.39   648.6 1095.32   658.7 1103.57   709.1 1138.54
#Mann= 3 , 0 , 0
       0      .1       0   235.9    .045       0   255.9     .06       0
Bank Sta=235.9,255.9
XS Rating Curve= 0 ,0
Exp/Cntr=0.3,0.1

Type RM Length L Ch R = 1 ,3257    ,179.2,182.3,185.4
XS GIS Cut Line= 4
     1637595.371      272778.013      1637411.51      272893.582
     1637266.173      273115.966     1637213.641      273445.165
#Sta/Elev= 30
     9.9 1085.93    29.6 1071.12    98.7 1035.56   108.6 1027.34   177.7  993.35
   197.4  978.77   217.2  967.68   236.8  960.63   256.5  945.61     286  913.13
   295.9  908.85   305.6  908.95   315.6  908.73   325.6  908.76   423.8  913.27
   433.6  914.47   453.3  921.92   463.2  922.89     473  926.59     503  943.63
   553.5  978.99   563.6  984.07   573.7   986.2   604.1 1009.37   654.6 1043.64
   664.7 1049.56   674.8 1050.61   765.7 1114.86   775.8 1115.37   816.2  1144.5
#Mann= 3 , 0 , 0
       0      .1       0   305.6    .045       0   325.6     .06       0
Bank Sta=305.6,325.6
XS Rating Curve= 0 ,0
Exp/Cntr=0.3,0.1

Type RM Length L Ch R = 1 ,3074.7  ,129.9,137.9,145.8
XS GIS Cut Line= 4
     1637313.451      272562.632     1637253.915      272818.287
     1637119.084      272977.633     1637059.548      273345.355
#Sta/Elev= 30
    10.1 1053.52    20.2  1049.8    40.4 1045.29    60.6 1036.97   121.2 1003.77
   141.3  998.81   181.7  978.82   222.1  962.93   232.2  959.71   242.3  959.67
   252.4  955.73   262.5  947.88   282.4  924.62   292.3  914.91   302.3  908.45
  327.65  903.27   332.1  902.55  347.71   902.6   481.3  913.21   531.6  929.73
   541.7  934.25   561.8  946.32     582  953.04   622.2  979.16   662.5  1008.1
   682.7 1015.88   763.2 1073.55   773.3 1079.39   783.3 1080.84   843.7 1123.44
#Mann= 3 , 0 , 0
    10.1      .1       0  327.65    .045       0  347.71     .06       0
Bank Sta=327.65,347.71
XS Rating Curve= 0 ,0
Exp/Cntr=0.3,0.1

Type RM Length L Ch R = 1 ,2936.8  ,128.2,129.4,130.6
XS GIS Cut Line= 4
     1637290.688      272562.632     1637171.616      272742.991
     1637007.016      272844.553     1636975.497      273224.532
#Sta/Elev= 30
     9.8 1042.93    29.5 1034.85    49.1 1024.18    58.9 1013.84    68.8 1005.59
   108.1  981.66     167  956.37   186.6  942.82   216.1  926.88   245.1  906.65
   254.8  903.68   293.2   897.1   303.2  896.75   313.2  897.47   332.2  900.33
   341.8   903.9   351.5  911.82   361.2  916.45   439.6  918.63   459.7  921.38
   489.8  929.43     560  936.07   570.1  938.54   620.2  963.15   640.3  969.03
   690.5 1002.31   720.6 1023.95   730.6 1029.84   740.6 1031.36   790.8 1067.42
#Mann= 3 , 0 , 0
       0      .1       0   293.2    .045       0   313.2     .06       0
Bank Sta=293.2,313.2
XS Rating Curve= 0 ,0
Exp/Cntr=0.3,0.1

Type RM Length L Ch R = 1 ,2807.4  ,179.8,176.3,172.7
XS GIS Cut Line= 4
      1637294.19      272531.113     1637148.852      272615.164
     1636924.717      272739.489     1636562.248      272935.608
#Sta/Elev= 30
     9.9 1049.74    39.5 1030.58    49.4 1019.31    59.3 1010.13    88.9  988.75
   118.5  969.13   138.3  947.94   148.1   941.5   217.2  901.97   266.3  894.75
   276.3  894.55   286.3  895.14     296  896.85   325.6  911.16   335.5     913
   384.8  917.48   454.4  915.91   464.4  918.73   484.5  930.66   504.6  939.06
   544.8  950.87   605.1  965.65   625.2  974.38   685.5  989.97   705.6  998.16
   735.8 1005.16     766 1015.09   786.1 1025.87   806.2 1034.08   836.3 1042.03
#Mann= 3 , 0 , 0
       0     .08       0   266.3    .045       0   286.3     .06       0
Bank Sta=266.3,286.3
XS Rating Curve= 0 ,0
Exp/Cntr=0.3,0.1

Type RM Length L Ch R = 1 ,2631.1  ,141.5,145.5,149.5
XS GIS Cut Line= 4
     1637290.688      272363.012     1637101.573      272419.046
     1636945.729      272536.367     1636562.248      272916.346
#Sta/Elev= 30
     9.9 1080.24    49.3 1052.67      69 1030.01   128.2  981.69   138.1  966.94
   167.7  943.33     207  923.58   216.7  916.25   255.8  899.95   275.3  895.76
   333.5  889.16   343.5  888.89   353.5  889.87   372.8  893.79   392.3  909.07
   402.3  909.93   432.3  904.68   452.3  904.03   522.3  910.21   552.3  924.96
   562.3     933   582.3  953.57   592.3  957.78   662.2  975.64   722.2  993.51
   792.2 1007.01   812.2 1006.87   852.2 1014.83   922.2  1040.4   932.2 1040.48
#Mann= 3 , 0 , 0
       0     .08       0   333.5    .045       0   353.5     .06       0
Bank Sta=333.5,353.5
XS Rating Curve= 0 ,0
Exp/Cntr=0.3,0.1

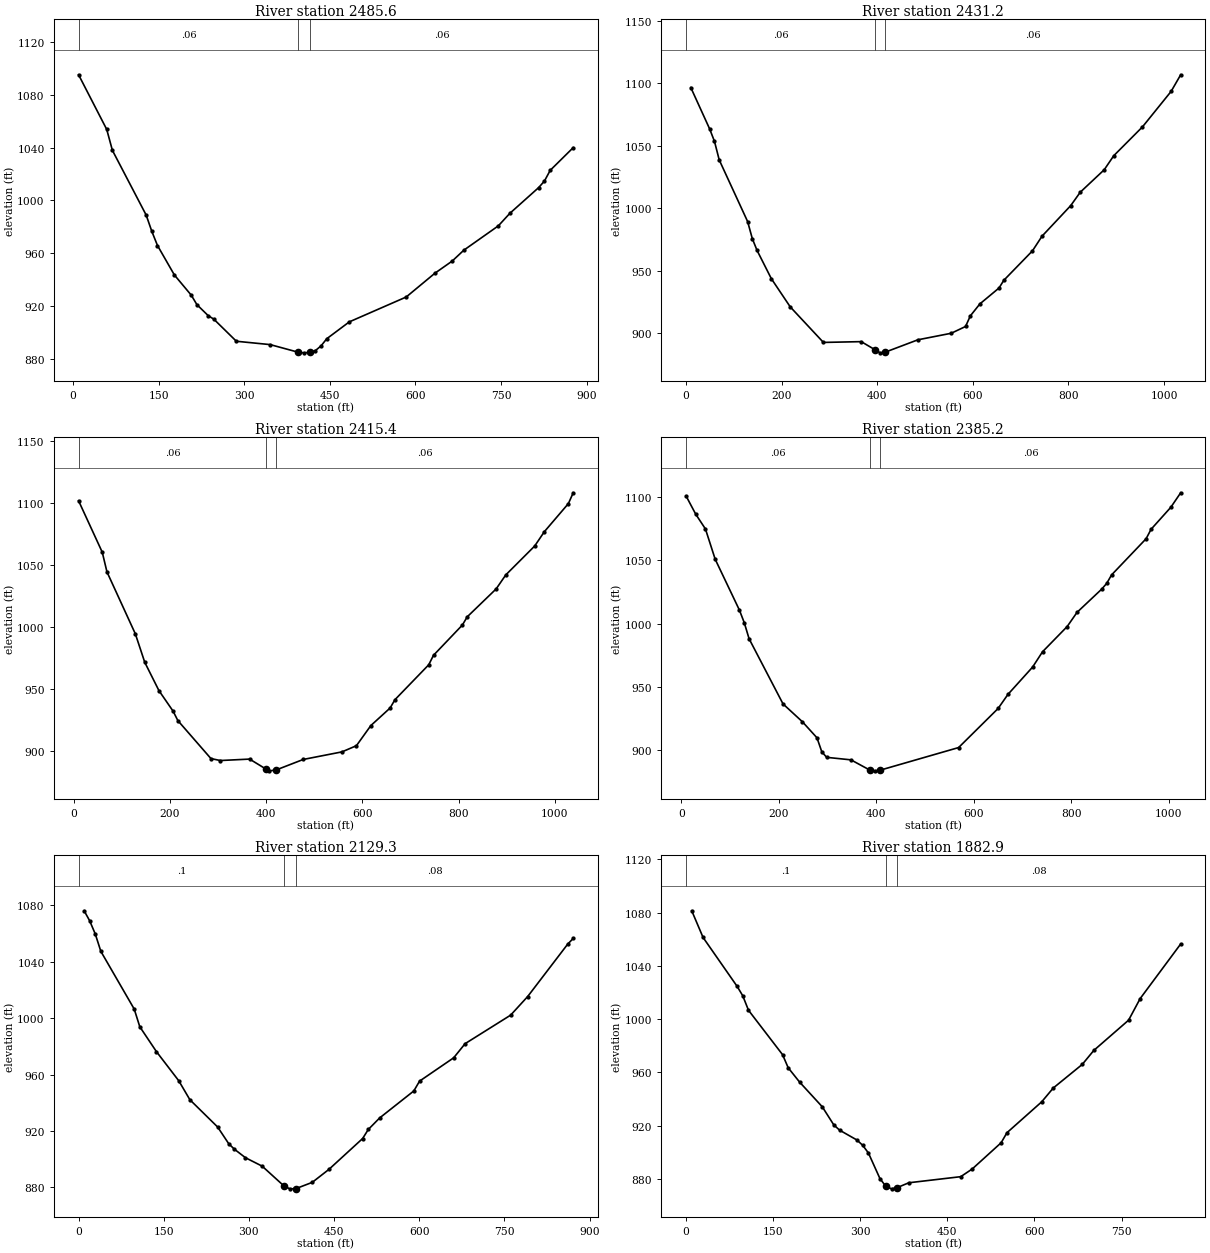
Type RM Length L Ch R = 1 ,2485.6  ,37.4,54.4,71.6
XS GIS Cut Line= 4
     1637285.199      272295.707     1636939.678      272379.034
     1636764.164      272470.861     1636459.589      272578.133
#Sta/Elev= 30
     9.9 1095.31    59.2 1053.89    69.1 1038.05   128.3  988.95   138.2  976.59
   148.1  965.88   177.7  943.55   207.3  928.22   217.2  921.03     237  912.69
   246.8  910.04   286.3  893.29   345.6  890.75   394.9  884.94   404.9  884.51
   414.9  884.85   424.8  886.23   434.7   889.8   444.6  895.19   484.2     908
   583.8  926.83   634.2   944.9   664.5  954.11   684.7  962.31   745.2  980.77
   765.4  990.27   815.9  1009.8     826 1014.76   836.1 1022.87   876.4 1040.08
#Mann= 3 , 0 , 0
     9.9     .06       0   394.9    .045       0   414.9     .06       0
#XS Ineff= 2 , 0
       0     365           430.5       0
Permanent Ineff=
       F       F
Bank Sta=394.9,414.9
XS Rating Curve= 0 ,0
Exp/Cntr=0.3,0.1

Type RM Length L Ch R = 1 ,2431.2  ,15.6,15.8,16
XS GIS Cut Line= 4
     1637283.763       272289.96     1636985.383      272363.028
     1636780.926      272327.314     1636263.004      272375.442
#Sta/Elev= 30
     9.9 1096.74    49.5 1063.46    59.5 1053.56    69.4 1038.74   128.8  989.39
   138.7  975.61   148.6  966.23   178.4  943.65     218  921.03   287.4  892.56
   366.5  893.19     396  886.56     406  884.22     416  884.66   485.1  894.67
   554.8   899.9   584.8  905.33   594.8  913.83   614.8  923.43   654.8  936.15
   664.8   942.3   724.8  965.92   744.8  977.67   804.8 1002.14   824.8 1012.88
   874.9 1030.86   894.9 1042.13   954.9 1065.19  1014.9 1093.64  1034.9 1106.94
#Mann= 3 , 0 , 0
       0     .06       0     396    .045       0     416     .06       0
Bank Sta=396,416
XS Rating Curve= 0 ,0
Exp/Cntr=0.3,0.1

Type RM Length L Ch R = 1 ,2415.4  ,33.4,30.2,27
XS GIS Cut Line= 4
     1637285.434      272282.463     1636988.211       272349.29
     1636788.827      272312.947     1636261.066      272371.767
#Sta/Elev= 30
     9.8 1101.74      59 1060.32    68.8 1044.44   127.8  994.54   147.4  971.57
   176.9  948.76   206.4  932.15   216.2  924.62     285     894   304.6  892.43
   365.4  893.59  399.85  885.45     406  884.12   420.1  884.75   476.9  893.29
   557.4  899.39   587.5  904.37   617.5   920.6   657.6  934.77   667.6  941.44
   737.8  969.56   747.8  977.24   807.9 1001.65   817.9 1008.23     878 1030.71
   898.1 1042.01   958.2  1065.3   978.2  1076.8  1028.3 1099.51  1038.3  1108.2
#Mann= 3 , 0 , 0
     9.8     .06       0  399.85    .045       0   420.1     .06       0
Bank Sta=399.85,420.1
XS Rating Curve= 0 ,0
Exp/Cntr=0.3,0.1

Type RM Length L Ch R = 1 ,2385.2  ,249,255.9,262.8
XS GIS Cut Line= 4
     1637282.326      272269.846       1636956.2      272305.763
     1636796.729      272294.988      1636264.44      272361.794
#Sta/Elev= 30
     9.9 1101.23    29.8 1086.71    49.7    1075    69.6 1051.04   119.3 1010.68
   129.3 1000.63   139.2  987.88   208.8  936.18   248.6     922   278.4  909.31
   288.3  898.21   298.3  893.79   348.1   891.8     388  883.44     398  883.08
     408  883.61   568.9  901.55   649.9  932.56   670.1  943.74   720.7  965.43
     741  977.55   791.6   997.6   811.8 1008.84   862.4 1027.28   872.6 1031.81
   882.7 1038.58   953.5 1067.29   963.7 1074.78  1004.2 1092.24  1024.4 1103.74
#Mann= 3 , 0 , 0
     9.9     .06       0     388    .045       0     408     .06       0
#XS Ineff= 2 , 0
       0     376             428       0
Permanent Ineff=
       F       F
Bank Sta=388,408
XS Rating Curve= 0 ,0
Exp/Cntr=0.3,0.1

Type RM Length L Ch R = 1 ,2129.3  ,257.7,246.4,235.1
XS GIS Cut Line= 4
      1637162.86      272103.855     1636900.202      272135.375
      1636698.83      272058.328     1636343.366       271895.48
#Sta/Elev= 30
     9.8 1076.13    19.6 1068.97    29.4 1059.66    39.2 1047.36      98 1006.42
   107.8  993.89   137.2  976.21   176.4  955.62     196  942.16   244.9  922.81
   264.5  910.93   274.3  907.11   293.9  901.04   323.3  895.06   362.3   880.8
   372.3  878.98   382.3  879.07   411.5  883.57   440.9  892.78   500.2  914.64
   510.2  921.07   530.3  929.28   590.4  948.39   600.5  955.35   660.6  971.89
   680.7  981.91   760.9 1002.14   790.9 1015.33   861.1 1052.33   871.1 1056.54
#Mann= 3 , 0 , 0
       0      .1       0   362.3    .045       0   382.3     .08       0
Bank Sta=362.3,382.3
XS Rating Curve= 0 ,0
Exp/Cntr=0.3,0.1

Type RM Length L Ch R = 1 ,1882.9  ,140.9,146,151.1
XS GIS Cut Line= 4
     1637201.384      271834.193     1636968.493       271862.21
      1636681.32      271884.973     1636352.121      271883.222
#Sta/Elev= 30
     9.8 1081.31    29.3 1061.27      88 1024.52    97.7 1017.44   107.5 1006.63
   166.2  973.26   175.9  963.41   195.5  952.69   234.6  934.11   254.4  920.55
   264.4  916.57   294.2  909.19   304.1  905.25     314  899.47   333.9   880.2
   343.8  874.55   353.8  872.51   363.8  873.47   383.6  877.07     473  881.64
   492.8  887.42   542.6  907.12   552.6  914.64   612.4  937.82   632.4  948.23
   682.3  965.94   702.2  976.45   762.1  999.17     782 1015.37   851.8 1056.37
#Mann= 3 , 0 , 0
       0      .1       0   343.8    .045       0   363.8     .08       0
Bank Sta=343.8,363.8
XS Rating Curve= 0 ,0
Exp/Cntr=0.3,0.1