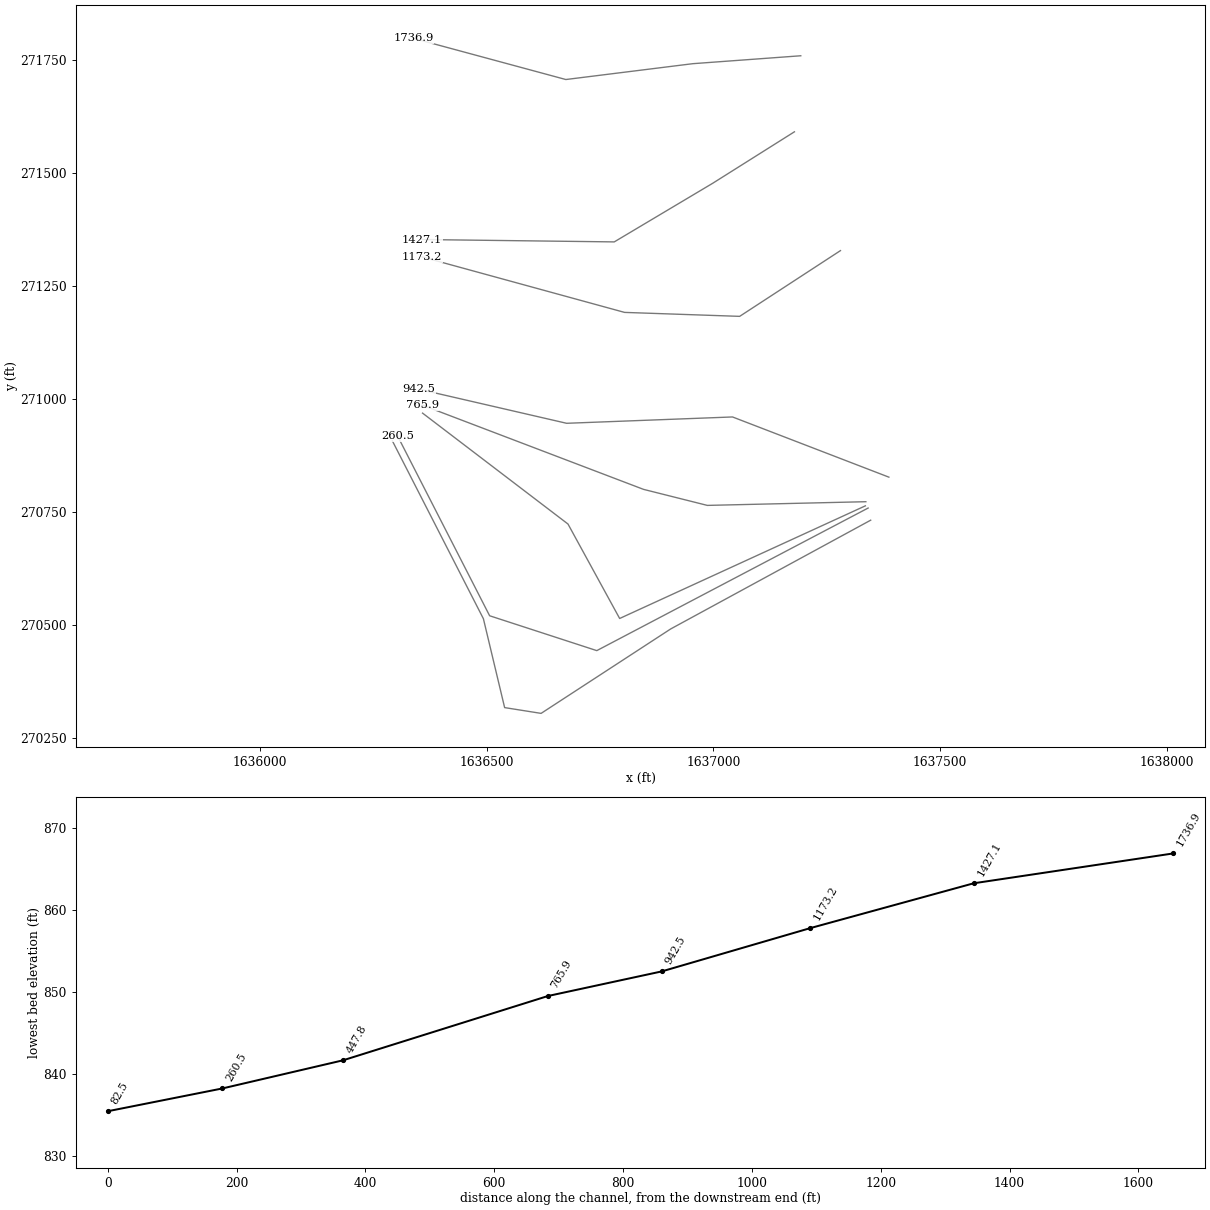
HEC-RAS study np1.prj: np1

--- np1.g01 (geometry) --- (continued)

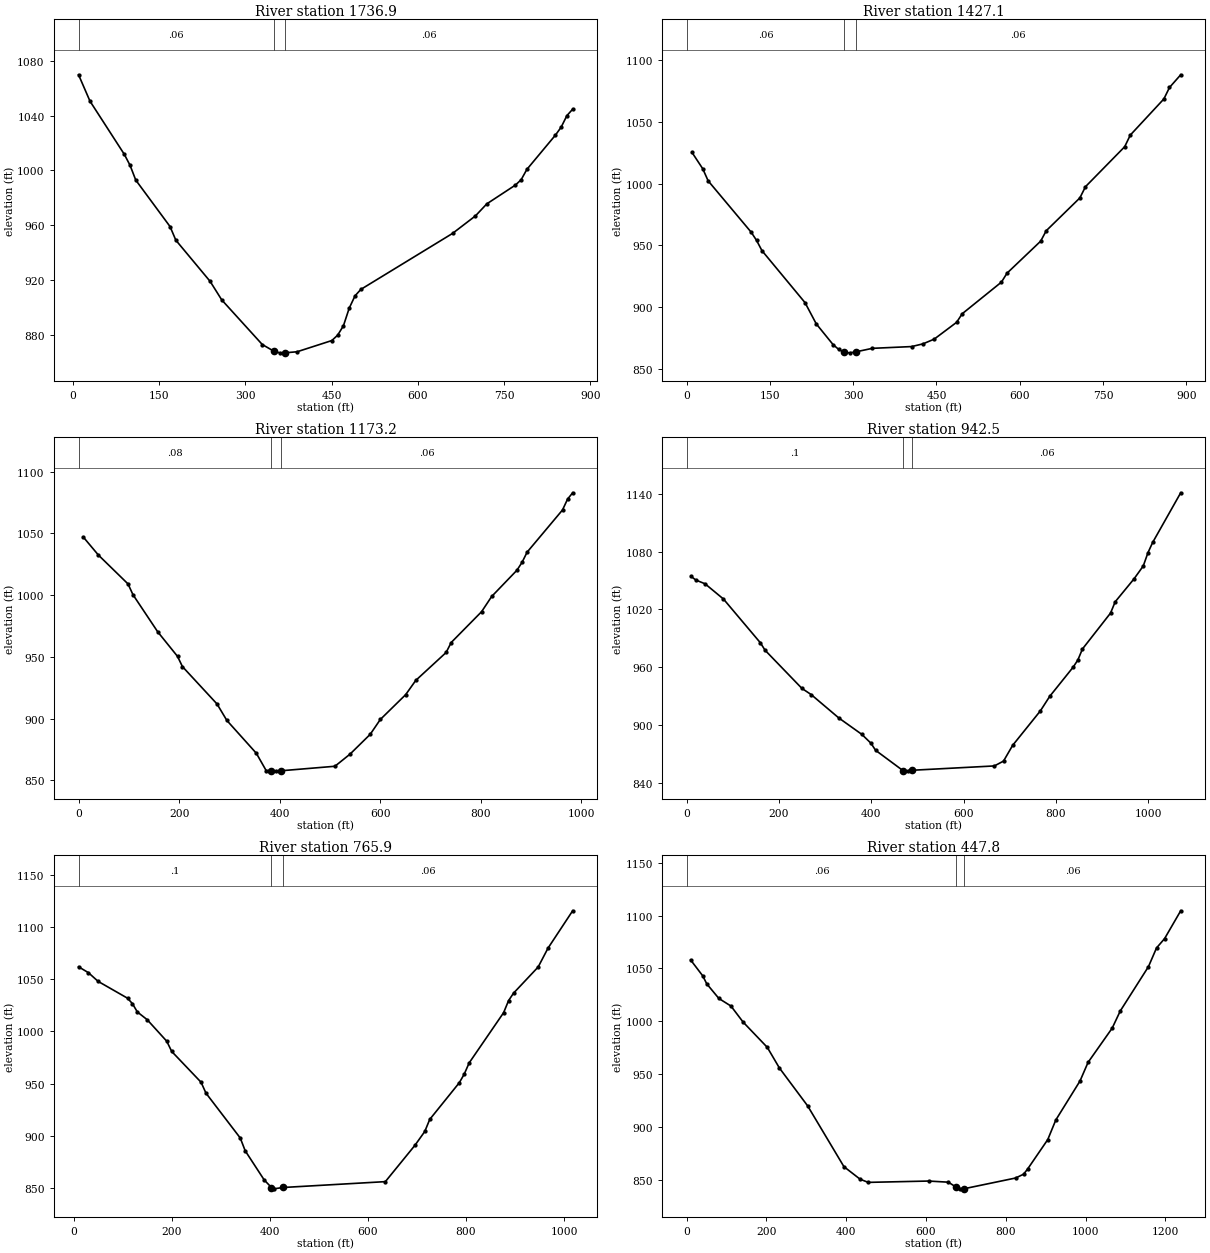
Type RM Length L Ch R = 1 ,1736.9  ,299.4,309.9,320.3
XS GIS Cut Line= 4
     1637192.628      271758.897     1636954.485      271741.387
     1636674.315      271706.366     1636338.112      271797.421
#Sta/Elev= 30
     9.9 1069.87    29.8 1050.59    89.5 1011.78    99.5 1003.74   109.4  992.99
   169.1  959.02   179.1  949.12   238.8  919.02     259   905.5   329.5  872.93
   349.8  868.02  359.96  866.85   369.8  866.91     390  867.63   450.5  875.82
   460.6  879.73   470.7  886.61   480.8  899.53   490.9  908.49     501  913.17
   660.5  954.04   700.3  966.82   720.2  975.65   769.9  989.34   779.9  993.26
   789.8 1000.77   839.6 1025.86   849.5 1031.65   859.5 1040.07   869.5 1044.75
#Mann= 3 , 0 , 0
     9.9     .06       0   349.8    .045       0   369.8     .06       0
Bank Sta=349.8,369.8
XS Rating Curve= 0 ,0
Exp/Cntr=0.3,0.1

Type RM Length L Ch R = 1 ,1427.1  ,268.3,253.9,239.5
XS GIS Cut Line= 4
      1637178.62      271590.796     1636998.261      271476.977
      1636781.13      271347.399     1636357.374      271352.652
#Sta/Elev= 30
     9.7 1025.19    29.1 1011.96    38.8 1002.21   116.3  960.71     126  954.09
   135.7   945.8   213.3  903.77   233.5  886.64   263.8  869.86     274  865.95
   284.2  863.55   294.2  863.21   304.2  863.95   334.6  866.85   405.4  868.28
   425.7  870.47   445.9  874.28   486.3  887.88   496.4  894.81     567  920.35
   577.1  927.59   637.7  953.47   647.7  961.88   708.3  988.42   718.4  997.48
     789 1029.78   799.1 1039.18   859.6  1068.4   869.7 1077.66   889.9 1087.92
#Mann= 3 , 0 , 0
       0     .06       0   284.2    .045       0   304.2     .06       0
Bank Sta=284.2,304.2
XS Rating Curve= 0 ,0
Exp/Cntr=0.3,0.1

Type RM Length L Ch R = 1 ,1173.2  ,228.8,230.6,232.5
XS GIS Cut Line= 4
     1637280.181      271328.137     1637057.797        271182.8
     1636803.894      271191.555     1636357.374      271314.129
#Sta/Elev= 30
     9.8 1046.83    39.4 1032.47    98.4 1009.06   108.2 1000.37   157.4  970.32
   196.8  950.43   206.6  942.14   275.4  911.88     295  898.53   353.6  871.97
   373.1  857.98   382.7  857.81   392.7  857.74   402.7   857.8   509.9  861.44
   539.9  871.24   580.1   887.3   600.2  899.32   650.6  919.41   670.7  930.95
   731.1  953.57   741.2  961.64   801.6  986.58   821.7  998.91     872 1020.19
   882.1 1026.53   892.2  1034.8   962.6 1068.96   972.7 1077.77   982.8 1082.87
#Mann= 3 , 0 , 0
       0     .08       0   382.7    .045       0   402.7     .06       0
Bank Sta=382.7,402.7
XS Rating Curve= 0 ,0
Exp/Cntr=0.3,0.1

Type RM Length L Ch R = 1 ,942.5   ,183.8,176.7,169.5
XS GIS Cut Line= 4
     1637386.996      270827.335     1637042.037      270960.415
     1636676.067      270946.407      1636350.37      271021.702
#Sta/Elev= 30
      10 1054.11      20 1050.45      40 1046.53    79.9 1030.71   159.9  985.27
   169.9  977.63   249.8  937.99   269.8  931.61   329.8  907.29   379.6  890.29
   399.4  881.08   409.3   873.8   468.6  852.74   478.6  852.46   488.6  853.06
   666.7  857.55   686.5  862.59   706.3  878.93   766.4  914.73   786.6  929.77
   837.3  960.03   847.4  967.37   857.5  978.94   918.3 1016.16   928.4 1027.88
     969 1051.55   989.2 1065.04   999.4 1078.84  1009.5  1089.4  1070.3 1140.98
#Mann= 3 , 0 , 0
       0      .1       0   468.6    .045       0   488.6     .06       0
Bank Sta=468.6,488.6
XS Rating Curve= 0 ,0
Exp/Cntr=0.3,0.1

Type RM Length L Ch R = 1 ,765.9   ,339.1,318.1,297.2
XS GIS Cut Line= 4
     1637336.215      270773.052     1636986.525      270764.892
     1636845.731       270800.33     1636357.374      270986.681
#Sta/Elev= 30
      10 1061.91      30  1056.3      50 1047.92   109.9 1031.85   119.9 1026.61
   129.9 1018.69   149.9 1011.32   189.9  990.68   199.9  980.95   259.8  951.47
   269.8  941.05   339.8  898.08   349.8  885.91   388.5  858.04  403.43  850.72
   407.9  849.46   427.2  850.75   635.7  856.35     696  891.09   716.1  904.35
   726.2   915.9   786.5  950.99   796.5  959.17   806.6  969.95   876.9 1018.05
     887 1029.57   897.1 1036.69   947.3 1061.69   967.4 1079.74  1017.7  1115.5
#Mann= 3 , 0 , 0
      10      .1       0  403.43    .045       0   427.2     .06       0
Bank Sta=403.43,427.2
XS Rating Curve= 0 ,0
Exp/Cntr=0.3,0.1

Type RM Length L Ch R = 1 ,447.8   ,168.6,187.2,205.9
XS GIS Cut Line= 4
     1637335.159      270763.934     1636793.053       270514.91
     1636679.076      270723.707     1636358.218        270968.9
#Sta/Elev= 30
    10.1 1058.02    40.4    1043    50.6 1035.38    80.9  1021.6   111.2 1014.42
   141.6  999.29   202.2  975.39   232.6  955.86   303.3  920.08   394.3  862.58
   434.8  850.74     455  847.73   606.5  848.99     656  847.91   675.8  843.16
   685.8  841.62   695.8  841.75   824.5  851.85   844.5  855.46   854.6  860.34
   905.1  888.17   925.3  906.73   985.9  943.56  1006.1  961.17  1066.6  993.57
  1086.8 1009.76  1157.5 1051.71  1177.7 1069.36  1197.9 1078.18  1238.3  1104.5
#Mann= 3 , 0 , 0
       0     .06       0   675.8    .045       0   695.8     .06       0
Bank Sta=675.8,695.8
XS Rating Curve= 0 ,0
Exp/Cntr=0.3,0.1

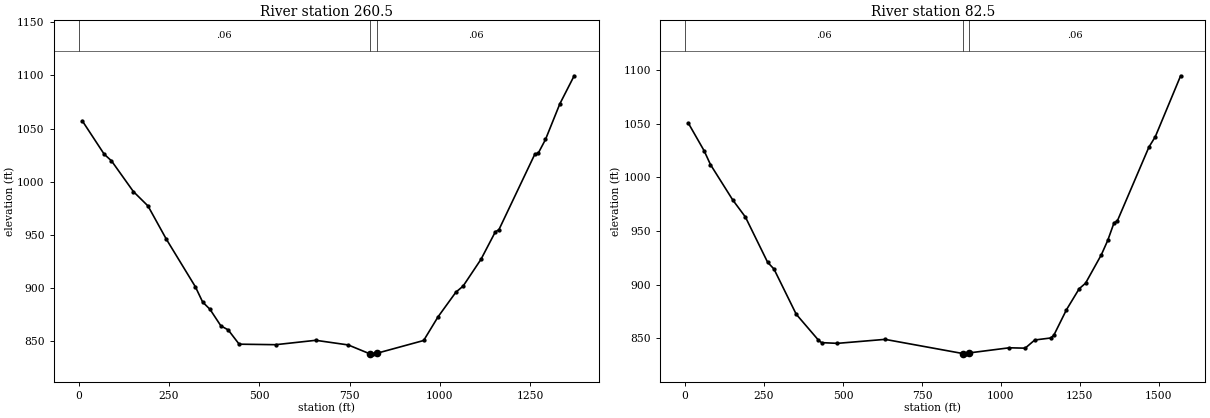
Type RM Length L Ch R = 1 ,260.5   ,174.1,178,182
XS GIS Cut Line= 4
     1637341.277      270759.085     1636742.607      270443.853
     1636506.214        270520.9     1636303.091       270918.39
#Sta/Elev= 30
    10.1 1057.32    70.7 1025.95    90.9  1019.7   151.5  990.81   191.9  977.29
   242.4  946.22   323.1  901.27   343.3  886.89   363.5   880.1   393.8  864.47
     414   860.7   444.3  847.27   545.3  846.79   656.4  850.92   746.2  846.56
   805.8  838.23   815.8  838.19   825.8  838.75     955  850.74   994.7  872.94
  1044.3  896.22  1064.1  901.85  1113.7  927.09  1153.4  952.92  1163.3  954.94
  1262.5 1025.81  1272.4 1027.04  1292.2 1039.76  1331.9 1073.26  1371.6 1099.68
#Mann= 3 , 0 , 0
       0     .06       0   805.8    .045       0   825.8     .06       0
Bank Sta=805.8,825.8
XS Rating Curve= 0 ,0
Exp/Cntr=0.3,0.1

Type RM Length L Ch R = 1 ,82.5    ,82.5,82.5,82.5
XS GIS Cut Line= 6
     1637346.858      270732.203     1636905.592      270491.741
     1636619.745      270305.124     1636539.291      270317.894
     1636492.466      270514.346     1636291.544      270907.677
#Sta/Elev= 30
    10.1 1050.82    60.3 1024.92    80.4 1012.02   150.8  979.07     191  963.08
   261.3  920.87   281.4  914.58   351.8   872.4   422.1  848.23   432.2  845.86
   482.4   845.2   633.1  848.92   879.2   835.7   889.2  835.41   899.2  836.26
  1026.3  841.05  1076.8  840.71  1107.1  848.33  1157.4   850.2  1167.5  852.77
  1207.6  876.63  1247.8  896.18  1267.9  901.33    1318  927.92  1338.1  941.23
  1358.2  957.76  1368.2   959.2  1468.6 1028.41  1488.7 1038.02    1569 1094.94
#Mann= 3 , 0 , 0
       0     .06       0   879.2    .045       0   899.2     .06       0
Bank Sta=879.2,899.2
XS Rating Curve= 0 ,0
Exp/Cntr=0.3,0.1

Chan Stop Cuts=-1
Use User Specified Reach Order=0